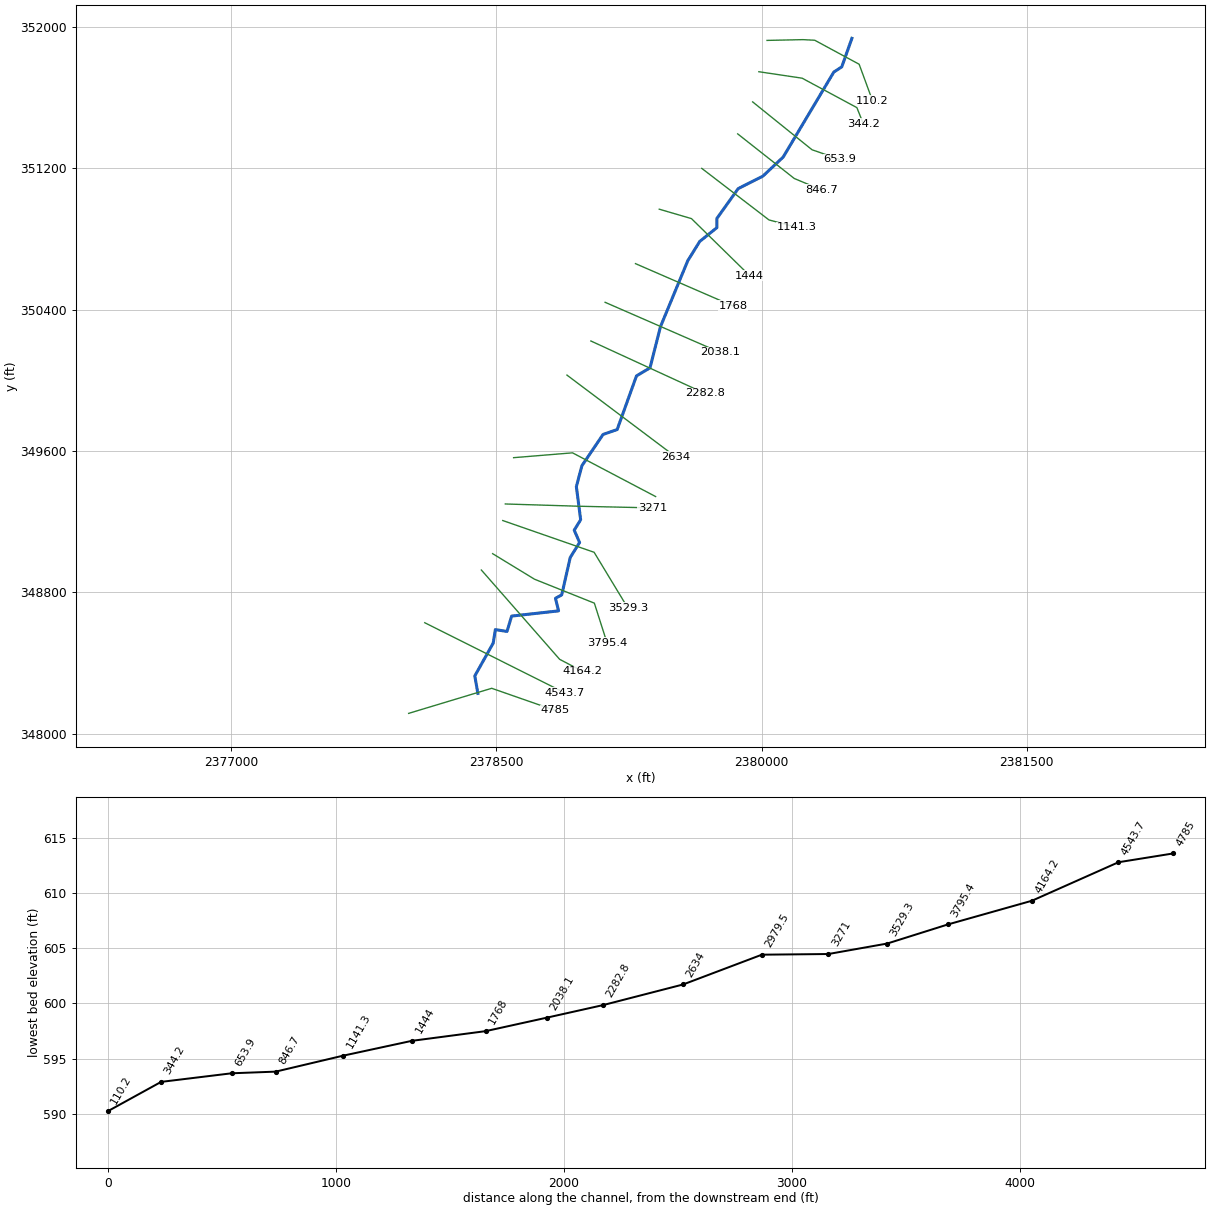
--- TUSCARORA1.prj (project) ---

Proj Title=TUSCARORA1
Current Plan=p01
Default Exp/Contr=0,0
English Units
Geom File=g01
Flow File=f01
Plan File=p01
BEGIN DESCRIPTION:
END DESCRIPTION:
DSS Export Rating Curves= 0
DSS Export Rating Curve Sorted= 0
DSS Export Volume Flow Curves= 0
DXF OffsetX= 0
DXF OffsetY= 0
DXF ScaleX= 0
DXF ScaleY= 0

--- TUSCARORA1.p01 (plan) ---

Plan Title=Floodplain
Program Version=4.00
Geom File=g01
Flow File=f01
K Sum by GR=0
Std Step Tol=0.01
Critical Tol=0.01
Num of Std Step Trials=20
Max Error Tol=0.3
Flow Tol Ratio=0.001
Split Flow NTrial=30
Split Flow Tol=0.02
Split Flow Ratio=0.02
Log Output Level=0
Friction Slope Method=1
Unsteady Friction Slope Method=2
Unsteady Bridges Friction Slope Method=1
Global Log Level=0
CheckData=False
Run HTab=0
Run UNet=0
Run PostProcess=0
UNET Theta=0
UNET Theta Warmup=0
UNET ZTol=0
UNET ZSATol=0
UNET MxIter=0
UNET MaxInSteps=0
UNET DtIC=0
UNET DtMin=0
UNET MaxCRTS=0
UNET WFStab=0
UNET SFStab=0
UNET WFX=0
UNET SFX=0
UNET DSS MLevel=0
UNET DZMax Abort=0
UNET Convert EG Bridges=0
UNET Use Existing IB Tables=0
UNET Froude Limit=0
UNET Froude Power=0
Write IC File=0
Echo Input=False
Echo Output=False
Write Detailed=0

--- TUSCARORA1.f01 (steady flow) ---

Flow Title=NFF Regression Equation
Program Version=5.03
Number of Profiles= 1
Profile Names=P100yr
River Rch & RM=TUSCARORA1,Main            ,4785
     250
Boundary for River Rch & Prof#=TUSCARORA1,Main            , 1
Up Type= 0
Dn Type= 1
Dn Known WS=593.4
DSS Import GetInterval= 0
DSS Import GetPeak= 0
DSS Import FillOption= 0

--- TUSCARORA1.g01 (geometry) ---

Geom Title=USGS 10m DEM
Program Version=4.10

River Reach=TUSCARORA1      ,Main
Reach XY= 30
     2378394.712      348227.871      2378377.35       348326.83
     2378481.517      348512.593      2378493.67      348588.982
     2378559.642      348578.566     2378585.684      348665.371
     2378851.309      348694.885     2378833.948      348766.066
     2378869.188       348785.46     2378917.281      348996.968
     2378970.305      349081.791     2378939.851      349151.482
     2378976.309       349210.51     2378952.003       349398.01
     2378983.253      349516.066     2379103.045      349693.149
     2379182.906      349720.927     2379292.281      350024.746
      2379368.67      350069.885     2379427.698      350302.524
     2379582.212      350675.788      2379649.92      350785.163
     2379747.142      350863.288     2379747.142      350915.371
     2379867.635      351084.058     2380007.559      351154.954
     2380122.142      351262.593     2380408.601      351743.496
     2380453.739       351773.01     2380511.031      351934.468

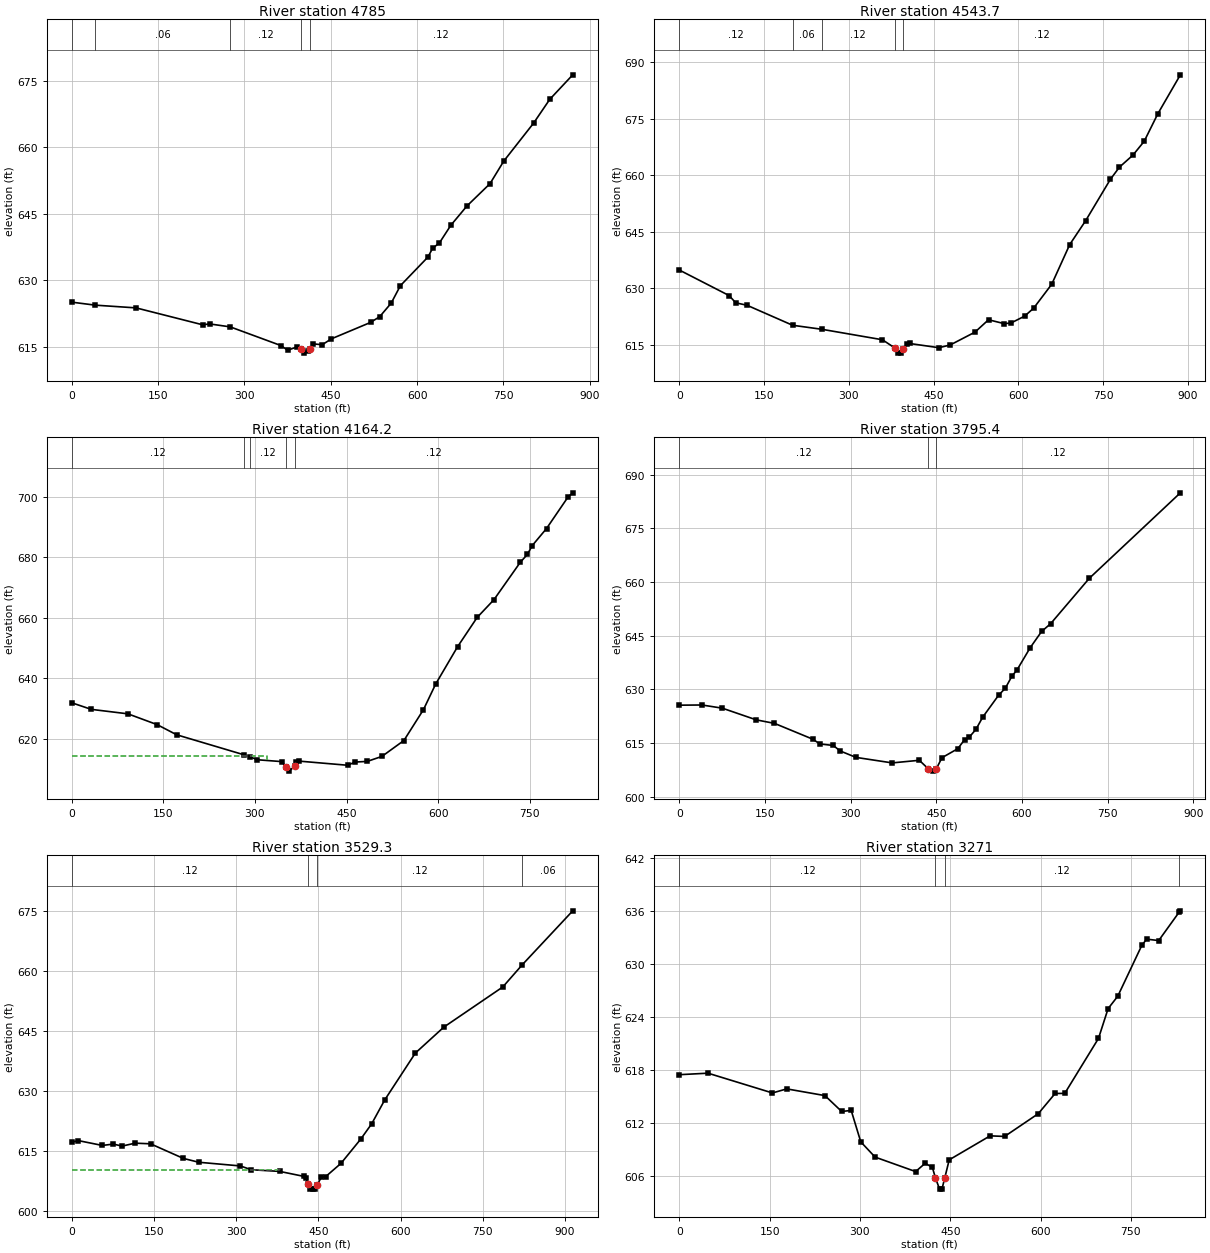
Type RM Length L Ch R = 1 ,4785    ,258,241.2,223.6
XS GIS Cut Line= 3
     2378002.977      348114.935     2378473.029      348256.862
     2378831.102      348131.862
#Sta/Elev= 30
       0  625.08   41.06624.4023   111.8  623.79   227.5  619.98   239.5  620.18
  275.37619.5114   363.3  615.31   375.2  614.25   391.2     615  397.47  614.55
   403.2   613.6   411.2     614  413.15  614.58   419.2  615.69   435.1  615.49
   451.1  616.82     519  620.51   534.9   621.8   554.9  624.85   570.9  628.79
   618.8  635.24   626.8   637.2   638.7  638.42   658.7  642.42   686.6  646.75
   726.6  651.77   750.5  656.85   802.4  665.42   830.4  670.76   870.3  676.28
#Mann= 5 ,-1 , 0
       0     .12       0   41.06     .06       0  275.37     .12       0
  397.47    .045       0  413.15     .12       0
Bank Sta=397.47,413.15
XS Rating Curve= 0 ,0
Exp/Cntr=0.3,0.1

Type RM Length L Ch R = 1 ,4543.7  ,384.9,379.5,369.5
XS GIS Cut Line= 2
     2378094.123      348627.956     2378887.092       348230.82
#Sta/Elev= 30
       0  634.86    87.9   628.1    99.9  626.16   119.8  625.51  200.52620.1972
  251.99619.1364   359.5  616.35   381.6  614.15   387.5  612.82   391.5   612.8
   396.6  613.82   403.5  615.28   407.5  615.36   459.4  614.24   479.4  614.96
   523.3  618.37   547.3  621.66   575.3  620.62   587.2  620.81   611.2  622.62
   627.2  624.74   659.2  631.09   691.1  641.64   719.1  647.93     763  658.94
     779  662.17     803  665.38   822.9  669.05   846.9  676.32   886.9  686.69
#Mann= 5 ,-1 , 0
       0     .12       0  200.52     .06       0  251.99     .12       0
   381.6    .045       0   396.6     .12       0
Bank Sta=381.6,396.6
XS Rating Curve= 0 ,0
Exp/Cntr=0.3,0.1

Type RM Length L Ch R = 1 ,4164.2  ,358.8,368.9,370.8
XS GIS Cut Line= 3
     2378414.436      348926.133     2378857.144      348420.925
     2378988.654      348351.914
#Sta/Elev= 30
       0  631.93      32  629.75      92  628.27   139.9  624.69   171.9  621.33
  282.12614.7058   292.2614.0252   303.9  613.07   343.9  612.46  350.37  610.82
   355.9  609.31  364.78  610.89   367.8  612.47   371.8  612.63   451.8  611.25
   463.8  612.31   483.8  612.53   507.8  614.18   543.8  619.44   575.8  629.65
   595.8  638.12   631.8  650.52   663.7  660.16   691.3  666.06   734.3   678.4
     746  681.04   753.8  683.92   777.3  689.59   812.4  699.99   820.2   701.4
#Mann= 5 ,-1 , 0
       0     .12       0  282.12    .016       0   292.2     .12       0
  350.37    .045       0  364.78     .12       0
#XS Ineff= 2 , 0
          319.31   614.2
Permanent Ineff=
       F       F
Bank Sta=350.37,364.78
XS Rating Curve= 0 ,0
Exp/Cntr=0.3,0.1

Type RM Length L Ch R = 1 ,3795.4  ,264.6,266,268.6
XS GIS Cut Line= 4
     2378478.238      349018.581     2378715.217       348874.05
     2379053.758      348738.633     2379125.373      348514.675
#Sta/Elev= 30
       0   625.6    39.6  625.65    75.3  624.76   134.8  621.49   166.6  620.51
     234  616.07   245.8  614.77   269.6  614.33   281.5  612.81   309.3     611
   372.7  609.46   420.2  610.19   436.1  607.78     444  607.16  449.91   607.8
   459.9  610.92   487.6  613.43   499.5  615.98   507.4  616.62   519.3  618.82
   531.2  622.25     559  628.37   570.9  630.37   582.8  633.84   590.7   635.3
   614.4  641.68   634.3   646.2   650.2  648.39   717.9  661.08   877.3  684.97
#Mann= 3 ,-1 , 0
       0     .12       0   436.1    .045       0  449.91     .12       0
Bank Sta=436.1,449.91
XS Rating Curve= 0 ,0
Exp/Cntr=0.3,0.1

Type RM Length L Ch R = 1 ,3529.3  ,247,258.3,264.8
XS GIS Cut Line= 3
     2378535.529      349206.081     2379052.456      349026.393
     2379242.561      348712.591
#Sta/Elev= 30
       0  617.16      12  617.56    55.9  616.35    75.9  616.69    91.9  616.19
   115.8  616.92   143.8  616.76   203.7  613.11   231.7  612.15   307.6  611.23
   327.6  610.28   379.5  609.86   423.4  608.62   427.4  608.33   431.4  606.64
   435.4  605.56   439.4  605.43   443.4   605.5   447.4  606.39   455.4  608.37
   463.4  608.56   491.3  611.87   527.3  617.92   547.3  621.75   571.2  627.74
     627  639.44   678.9  645.92   786.6  655.97  821.87661.4818   914.2     675
#Mann= 4 ,-1 , 0
       0     .12       0   431.4    .045       0   447.4     .12       0
  821.87     .06       0
#XS Ineff= 2 , 0
          379.44  610.16
Permanent Ineff=
       F       F
Bank Sta=431.4,447.4
XS Rating Curve= 0 ,0
Exp/Cntr=0.3,0.1

Type RM Length L Ch R = 1 ,3271    ,301.6,291.5,280.5
XS GIS Cut Line= 3
      2378549.88      349299.753     2378969.878      349286.875
     2379381.648      349277.613
#Sta/Elev= 30
       0  617.45    47.6  617.62   154.6  615.38   178.4  615.84   241.8  615.08
   269.6  613.28   285.4   613.4   301.3  609.84   325.1  608.11   392.4  606.47
   408.3  607.41   420.2  606.95  425.28  605.76   432.2  604.48   436.2   604.5
  440.93  605.78   448.2   607.8   516.2  610.52   540.2  610.45   596.1  613.03
   624.1  615.32   640.1  615.33   696.1  621.56   712.1  624.94   728.1  626.34
   768.1  632.11   776.1  632.81   796.1  632.65  829.93635.8572   832.1  636.02
#Mann= 4 ,-1 , 0
       0     .12       0  425.28    .045       0  440.93     .12       0
  829.93     .06       0
Bank Sta=425.28,440.93
XS Rating Curve= 0 ,0
Exp/Cntr=0.3,0.1

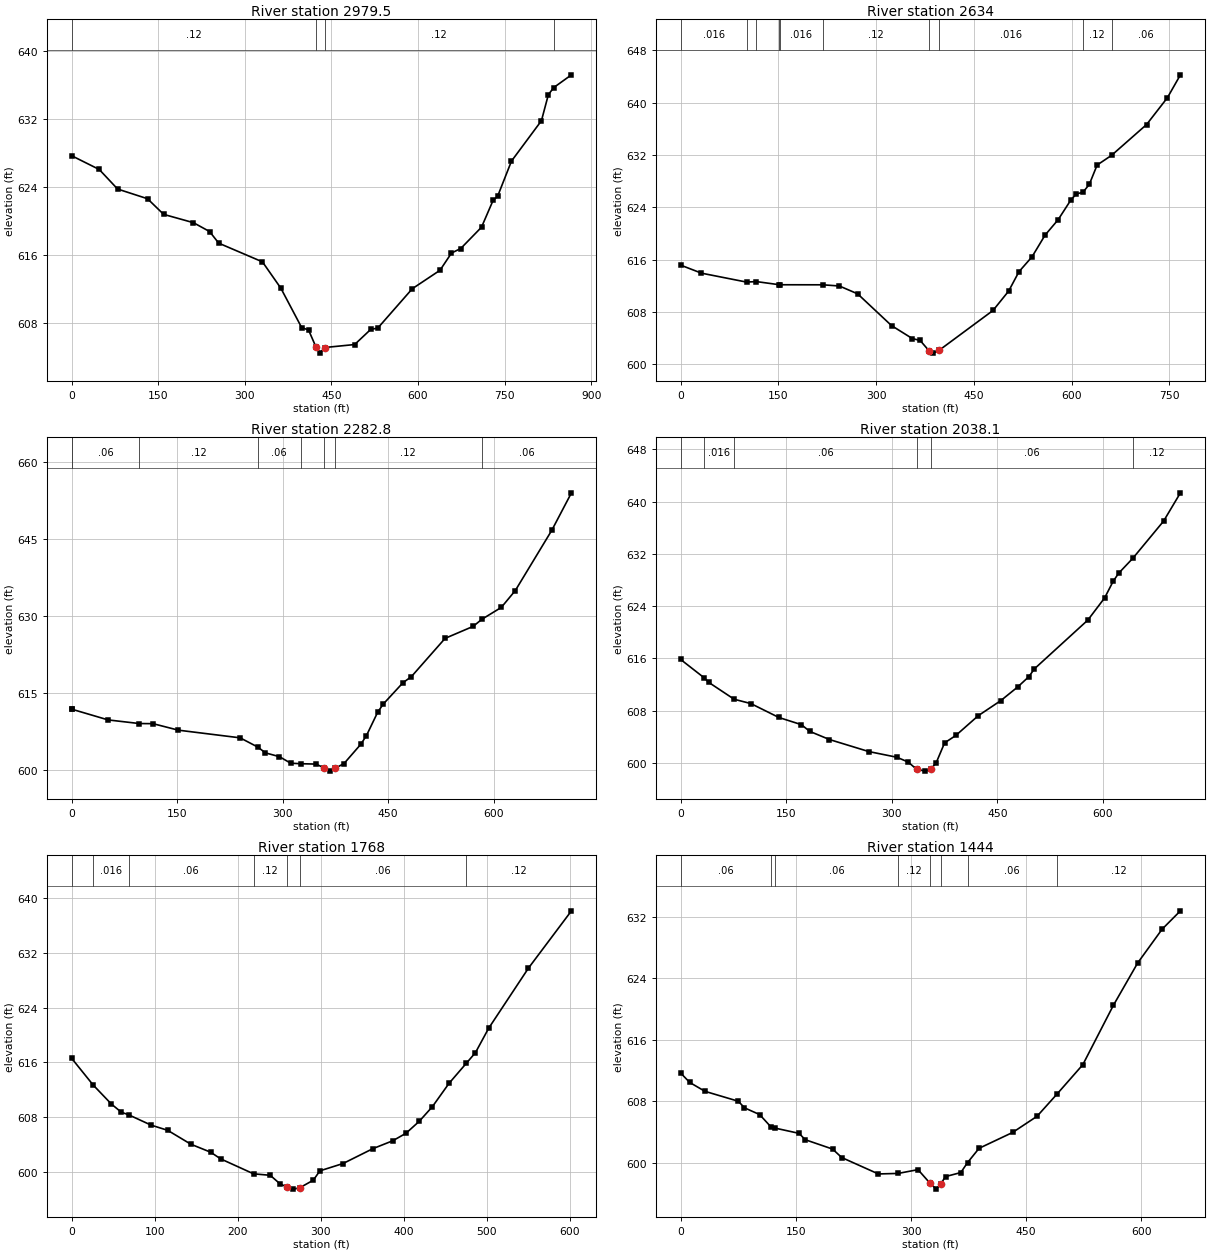
Type RM Length L Ch R = 1 ,2979.5  ,349.8,345.6,340.7
XS GIS Cut Line= 3
     2378596.944      349561.767     2378930.278       349589.11
     2379400.503      349341.751
#Sta/Elev= 30
       0  627.65    47.8  626.03    79.6  623.73   131.4  622.59   159.3  620.75
     211  619.77   238.9  618.73   254.8  617.36   330.5  615.16   362.4  612.06
   398.4  607.43   410.4  607.14  423.27  605.13   430.3  604.42   438.3  605.08
   490.2  605.43   518.2  607.22   530.2  607.36   590.1     612   638.1  614.17
     658   616.2     674  616.73     710  619.24     730  622.39   737.9  622.88
   761.9  627.02   813.8  631.77   825.8  634.84   835.2635.6755   865.8  637.17
#Mann= 4 ,-1 , 0
       0     .12       0  423.27    .045       0   438.3     .12       0
   835.2     .06       0
Bank Sta=423.27,438.3
XS Rating Curve= 0 ,0
Exp/Cntr=0.3,0.1

Type RM Length L Ch R = 1 ,2634    ,341,351.2,354.4
XS GIS Cut Line= 2
     2378898.811      350028.998     2379512.092       349568.06
#Sta/Elev= 30
       0  615.17      32  613.94  101.21612.5767   116.2612.6547  151.45 612.173
  152.67612.1691  218.14612.1608   243.7  611.98   271.7  610.78   323.7  605.93
   355.6  603.95   367.6  603.66  381.23  602.09   387.6  601.72   396.5  602.13
   479.5  608.24   503.5   611.2   519.4  614.17   539.4  616.44   559.4  619.75
   579.4   622.1   599.4  625.18   607.4  626.04  617.57626.3036   627.3   627.5
   639.3  630.46  661.64631.9572   715.2  636.65   747.2  640.75   767.2  644.25
#Mann= 10 ,-1 , 0
       0    .016       0  101.21     .12       0   116.2    .016       0
  151.45     .12       0  152.67    .016       0  218.14     .12       0
  381.23    .045       0   396.5    .016       0  617.57     .12       0
  661.64     .06       0
Bank Sta=381.23,396.5
XS Rating Curve= 0 ,0
Exp/Cntr=0.3,0.1

Type RM Length L Ch R = 1 ,2282.8  ,250.3,244.7,244.9
XS GIS Cut Line= 2
     2379033.967      350222.096       2379679.8      349925.221
#Sta/Elev= 30
       0   611.9      .9 611.855    51.9   609.8   96.14609.0983   115.8  609.07
   151.7  607.81   239.6  606.32  264.97604.5056   275.5   603.4   295.5  602.66
   311.5  601.39  325.53601.2913   347.4  601.22   359.3  600.47   367.4  599.85
   374.3  600.37   387.4  601.33   411.3  605.08   419.3  606.77   435.3  611.32
   443.2  612.89   471.2  617.03   483.2  618.22   531.1  625.65     571  627.98
  583.33629.3505     611  631.66   630.9  634.93   682.8  646.64   710.8  653.93
#Mann= 8 ,-1 , 0
       0    .016       0      .9     .06       0   96.14     .12       0
  264.97     .06       0  325.53     .12       0   359.3    .045       0
   374.3     .12       0  583.33     .06       0
Bank Sta=359.3,374.3
XS Rating Curve= 0 ,0
Exp/Cntr=0.3,0.1

Type RM Length L Ch R = 1 ,2038.1  ,270.1,270.1,270.2
XS GIS Cut Line= 2
     2379114.696      350440.846     2379765.738      350156.992
#Sta/Elev= 30
       0  615.83   33.79612.9904    39.9  612.32   76.05609.7331    99.8  609.07
   139.6  606.94   171.6  605.84   183.5  604.81   211.5  603.56   267.3  601.72
   307.2  600.85   323.2  600.12   335.2  599.02   347.1  598.72   355.1  598.98
   363.1  599.99   375.1  603.05     391  604.18     423  607.22   454.9  609.52
   478.8   611.6   494.8  613.19   502.8   614.4   578.6  621.86   602.5  625.26
   614.5  627.78   622.4  629.04  642.54631.3289   686.3  637.03   710.2  641.36
#Mann= 6 ,-1 , 0
       0     .06       0   33.79    .016       0   76.05     .06       0
   335.2    .045       0   355.1     .06       0  642.54     .12       0
Bank Sta=335.2,355.1
XS Rating Curve= 0 ,0
Exp/Cntr=0.3,0.1

Type RM Length L Ch R = 1 ,1768    ,332.5,324,315.2
XS GIS Cut Line= 2
     2379286.571      350659.596     2379838.654      350420.013
#Sta/Elev= 30
       0  616.59   25.76612.7124    47.8  609.92    59.8  608.72   68.46608.3527
    95.6  606.84   115.6  606.08   143.5  604.05   167.4  602.88   179.4  601.91
  219.02599.7249   239.1  599.51   251.1  598.24   259.4  597.81     267  597.49
   274.4  597.67     291   598.8   298.9  600.16   326.8  601.23   362.7   603.4
   386.6  604.55   402.6  605.65   418.5  607.39   434.4  609.54   454.4  612.94
  475.35615.8876   486.2  617.42   502.2     621     550  629.76   601.8  638.13
#Mann= 7 ,-1 , 0
       0     .06       0   25.76    .016       0   68.46     .06       0
  219.02     .12       0   259.4    .045       0   274.4     .06       0
  475.35     .12       0
Bank Sta=259.4,274.4
XS Rating Curve= 0 ,0
Exp/Cntr=0.3,0.1

Type RM Length L Ch R = 1 ,1444    ,302,302.7,297.6
XS GIS Cut Line= 3
     2379420.946        350967.8     2379603.238      350914.414
     2379932.404      350591.888
#Sta/Elev= 30
       0  611.69    11.9  610.46    31.7  609.31    75.2  608.02    83.1  607.17
   102.9  606.29  118.08604.6375  123.15604.5315   154.3  603.85   162.2  603.03
   197.9  601.81   209.8  600.71   257.5  598.58  283.28598.6499   309.1  599.14
     325  597.35     333  596.61  338.95  597.32   344.9  598.24   364.8  598.76
  373.58600.0526   388.6  601.91   432.3  603.97   464.1  606.07  490.08608.9526
   523.7  612.77   563.4  620.46   595.2  625.99     627  630.37   650.8  632.75
#Mann= 8 ,-1 , 0
       0     .06       0  118.08     .12       0  123.15     .06       0
  283.28     .12       0     325    .045       0  338.95     .12       0
  373.58     .06       0  490.08     .12       0
Bank Sta=325,338.95
XS Rating Curve= 0 ,0
Exp/Cntr=0.3,0.1

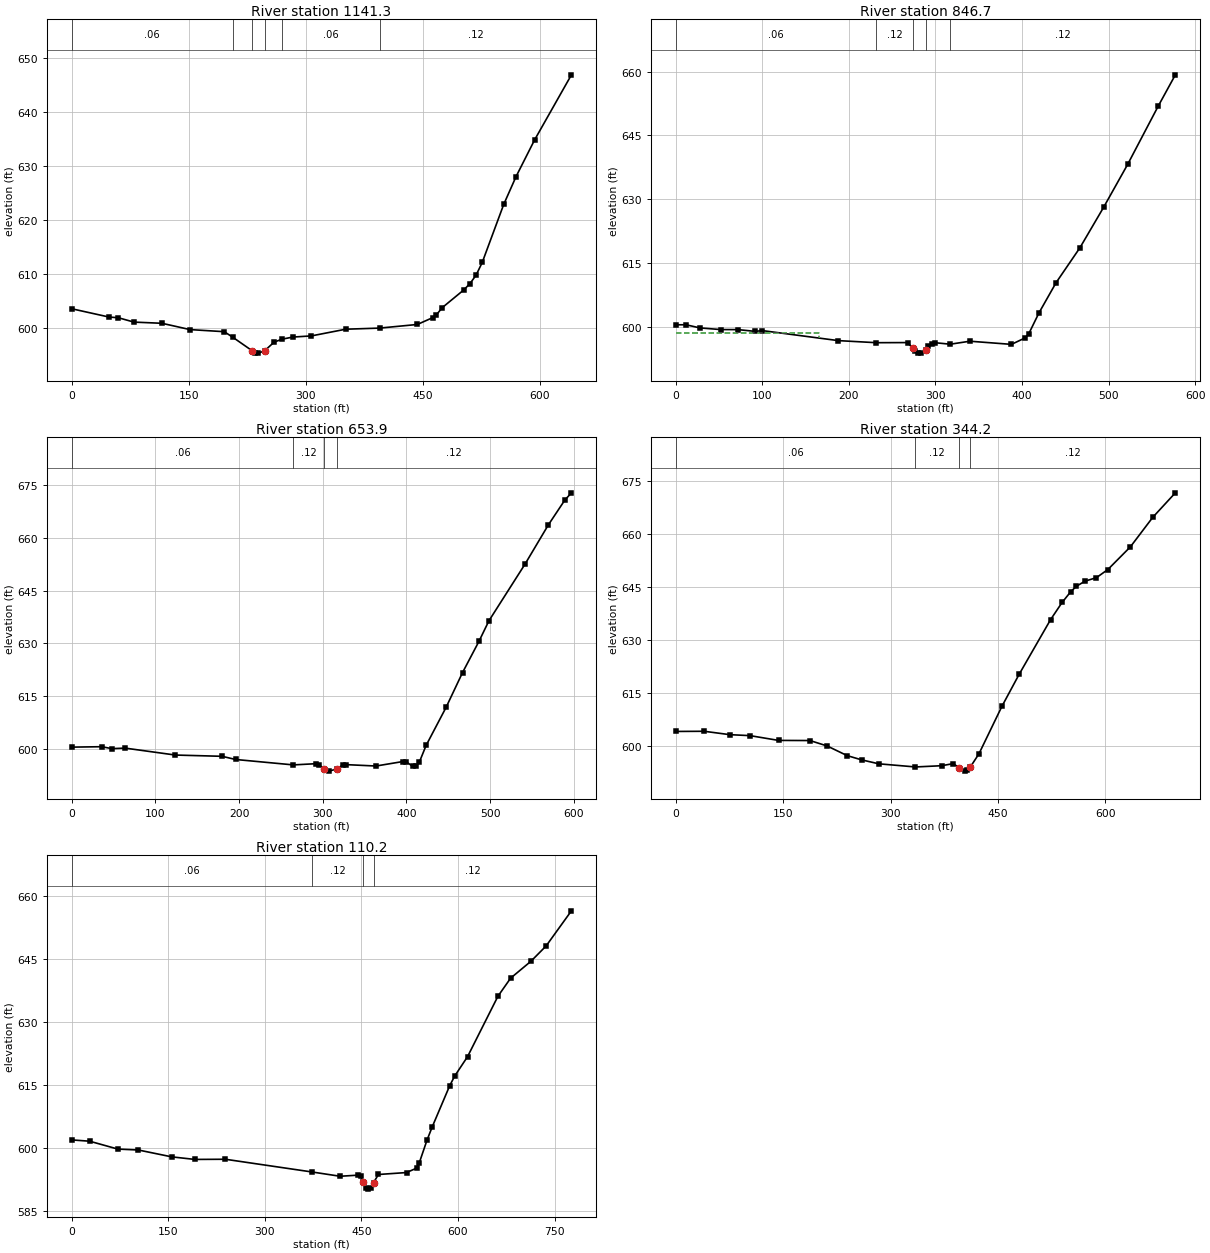
Type RM Length L Ch R = 1 ,1141.3  ,294.6,294.5,296.8
XS GIS Cut Line= 3
     2379661.571      351198.659     2380041.779      350906.992
     2380198.029      350865.326
#Sta/Elev= 30
       0   603.5    47.9  601.96    59.9  601.83    79.9  601.02   115.8   600.8
   151.8  599.63   195.7  599.24  206.69598.2014   231.6  595.69   235.6  595.29
   239.6  595.26   247.6  595.71   259.6   597.3  269.76597.8465   283.5  598.24
   307.5  598.46   351.4   599.7  394.93599.9081   443.3  600.58   463.2  601.86
   467.2  602.27   475.2   603.7   502.9     607   510.8  608.17   518.6  609.73
   526.5  612.09   554.1  622.88   569.9  628.04   593.6  634.83   640.9  646.93
#Mann= 6 ,-1 , 0
       0     .06       0  206.69     .12       0   231.6    .045       0
   247.6     .12       0  269.76     .06       0  394.93     .12       0
Bank Sta=231.6,247.6
XS Rating Curve= 0 ,0
Exp/Cntr=0.3,0.1

Type RM Length L Ch R = 1 ,846.7   ,192.8,192.9,192.3
XS GIS Cut Line= 3
     2379864.696      351393.971     2380185.008      351141.367
     2380341.258      351076.263
#Sta/Elev= 30
       0  600.48      12  600.49      28  599.75      52  599.36      72  599.35
      92  598.93     100  599.12     188  596.76  231.83 596.273     268   596.3
   273.9  594.96     276  594.38     280  593.89     284  593.82   288.9  594.59
     292  595.46     296  596.08     300  596.26  317.26595.9188   339.9  596.62
   387.9  595.88   403.9  597.42   407.9  598.37   419.7  603.29   439.4  610.37
     467   618.6   494.5  628.16   522.1  638.19   557.5  651.93   577.2  659.25
#Mann= 5 ,-1 , 0
       0     .06       0  231.83     .12       0   273.9    .045       0
   288.9     .06       0  317.26     .12       0
#XS Ineff= 2 , 0
          165.94  598.51
Permanent Ineff=
       F       F
Bank Sta=273.9,288.9
XS Rating Curve= 0 ,0
Exp/Cntr=0.3,0.1

Type RM Length L Ch R = 1 ,653.9   ,305.5,309.7,313.9
XS GIS Cut Line= 3
     2379949.331      351574.961     2380285.269      351304.128
     2380441.519       351249.44
#Sta/Elev= 30
       0  600.49      36  600.61      48  600.06    63.9  600.21   123.9  598.24
   179.8  597.88   195.8  596.98   264.9 595.439   291.7  595.78   295.7  595.46
   301.7  594.28   307.6  593.67   316.7  594.29   323.6  595.36   327.6  595.52
   363.6  595.12   395.6  596.39   399.6  596.34   407.5  595.02   411.5  595.09
   415.5  596.29   423.5  600.98   447.3  611.77     467  621.68   486.7  630.59
   498.5  636.38   541.9  652.59   569.5  663.64   589.2  670.69   597.1  672.76
#Mann= 4 ,-1 , 0
       0     .06       0   264.9     .12       0   301.7    .045       0
   316.7     .12       0
Bank Sta=301.7,316.7
XS Rating Curve= 0 ,0
Exp/Cntr=0.3,0.1

Type RM Length L Ch R = 1 ,344.2   ,234.6,234,233
XS GIS Cut Line= 4
     2379984.488      351745.534     2380229.279      351709.076
     2380539.175      351542.409     2380575.633      351451.263
#Sta/Elev= 30
       0   604.1    39.9  604.15    75.8  603.19   103.8  602.92   143.7  601.57
   187.6  601.53   211.6  599.99   239.5  597.27   259.5  596.08   283.5  594.96
  334.81594.0683   371.4  594.42   387.4  595.01   395.4  593.91   403.4  592.89
   407.4  593.11   411.4  594.07   423.4  597.79   455.4  611.18   479.4  620.22
   523.4  635.71   539.4  640.54   551.4  643.56   559.4  645.12   571.4  646.56
   587.4  647.56   603.3  649.85   634.7  656.25   666.1  664.63   697.5  671.52
#Mann= 4 ,-1 , 0
       0     .06       0  334.81     .12       0   395.4    .045       0
   411.4     .12       0
Bank Sta=395.4,411.4
XS Rating Curve= 0 ,0
Exp/Cntr=0.3,0.1

Type RM Length L Ch R = 1 ,110.2   ,107.4,110.2,113.1
XS GIS Cut Line= 5
     2380030.677      351922.723     2380233.849      351927.133
     2380300.745      351923.632     2380551.961      351787.945
     2380627.977      351581.081
#Sta/Elev= 30
       0  601.93    27.9  601.62    71.7  599.75   103.6  599.53   155.4   597.9
   191.3  597.29   238.7  597.33  372.95594.3126   416.9  593.29   444.7  593.55
   448.7  593.25   452.6   591.9   456.6  590.52   460.6  590.23   464.5   590.5
   468.9   591.8   476.4  593.71     520  594.17   535.9  595.23   539.9  596.51
   551.8  601.86   559.7  604.94   587.2  614.86   595.1  617.17   614.8  621.72
     662  636.08   681.7  640.38   713.2  644.39   736.8  648.03   776.1  656.38
#Mann= 4 ,-1 , 0
       0     .06       0  372.95     .12       0   452.6    .045       0
   468.9     .12       0
Bank Sta=452.6,468.9
XS Rating Curve= 0 ,0
Exp/Cntr=0.3,0.1

Chan Stop Cuts=-1
Use User Specified Reach Order=0
Composite Channel Slope=5